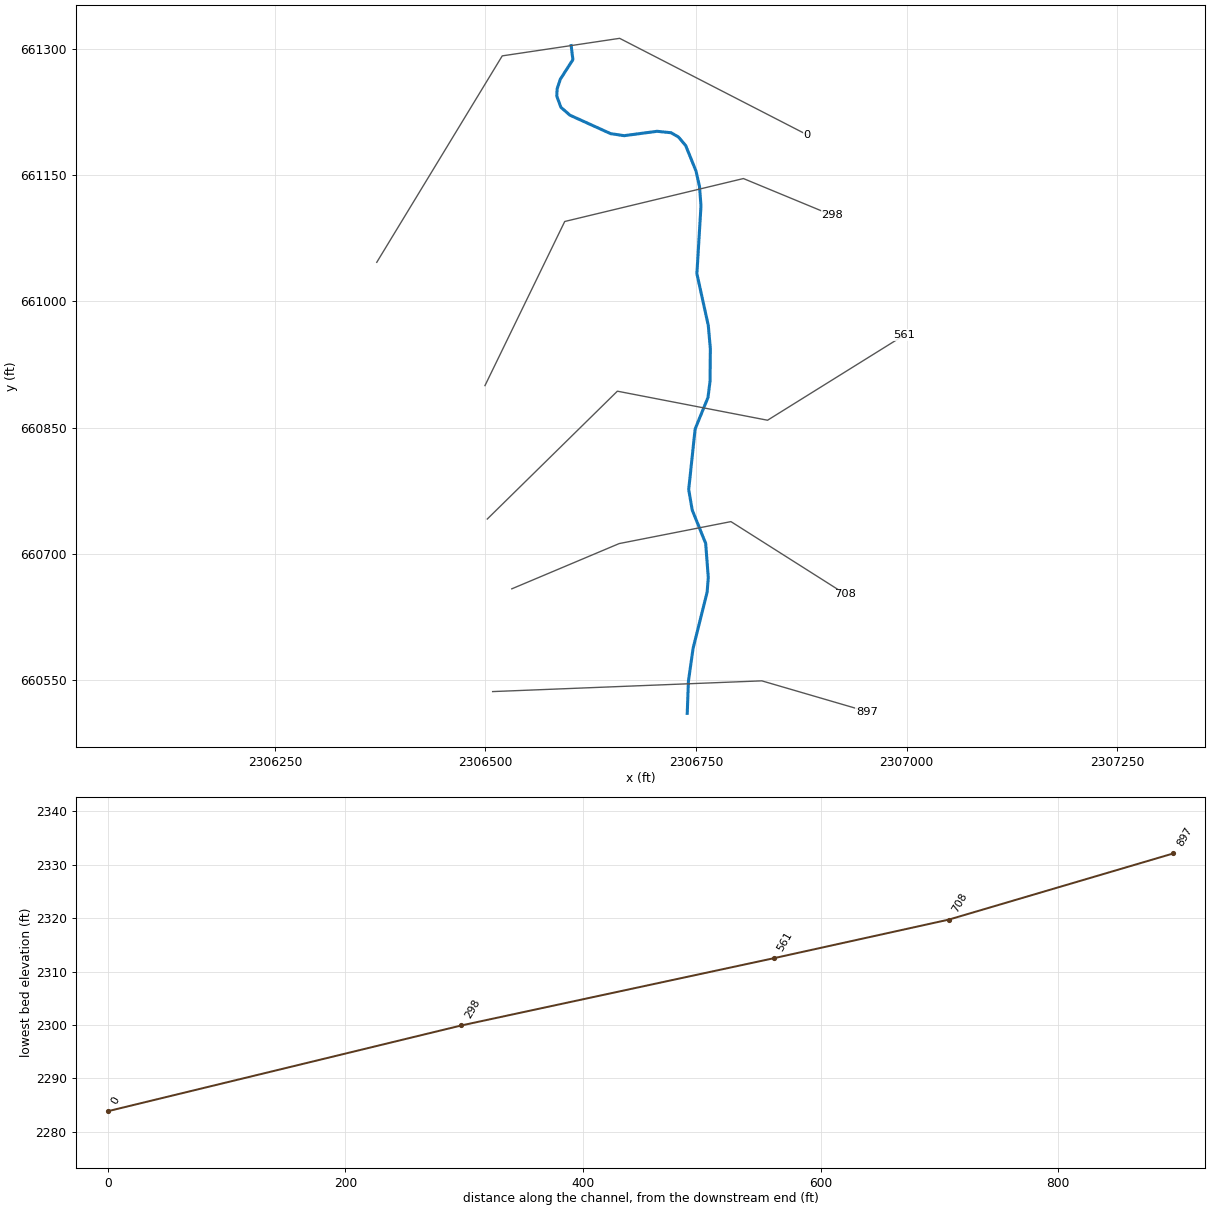
--- LIMKNRN2T1.prj (project) ---

Proj Title=LIMKNRN2T1
Current Plan=p01
Default Exp/Contr=0,0
English Units
Geom File=g01
Flow File=f01
Plan File=p01
BEGIN DESCRIPTION:
----------MODEL BY WOOD PLC 2022----------
AFH study
Randolph County, WV
HEC-RAS Version: RAS 6.2
Vertical Datum: NAVD88
Projection: NAD 1983 StatePlane West Virginia S FIPS 4702 (US Feet)
Terrain: 1-meter LIDAR (FEMA Region III 3DEP collected 2016-2018)
Land Use: 2019 NLCD
Hydrologic Method:
WV SIR2010-5033 regression equations
Additional Model Notes:
KWSE used because of stream orientation to DS stream. Not coincident peak
END DESCRIPTION:
DSS Export Rating Curves= 0
DSS Export Rating Curve Sorted= 0
DSS Export Volume Flow Curves= 0
DXF OffsetX= 0
DXF OffsetY= 0
DXF ScaleX= 0
DXF ScaleY= 0

--- LIMKNRN2T1.p01 (plan) ---

Plan Title=Floodplain
Program Version=4.00
Geom File=g01
Flow File=f01
K Sum by GR=0
Std Step Tol=0.01
Critical Tol=0.01
Num of Std Step Trials=20
Max Error Tol=0.3
Flow Tol Ratio=0.001
Split Flow NTrial=30
Split Flow Tol=0.02
Split Flow Ratio=0.02
Log Output Level=0
Friction Slope Method=1
Unsteady Friction Slope Method=2
Unsteady Bridges Friction Slope Method=1
Global Log Level=0
CheckData=False
Run HTab=0
Run UNet=0
Run PostProcess=0
UNET Theta=0
UNET Theta Warmup=0
UNET ZTol=0
UNET ZSATol=0
UNET MxIter=0
UNET MaxInSteps=0
UNET DtIC=0
UNET DtMin=0
UNET MaxCRTS=0
UNET WFStab=0
UNET SFStab=0
UNET WFX=0
UNET SFX=0
UNET DSS MLevel=0
UNET DZMax Abort=0
UNET Convert EG Bridges=0
UNET Use Existing IB Tables=0
UNET Froude Limit=0
UNET Froude Power=0
Write IC File=0
Echo Input=False
Echo Output=False
Write Detailed=0

--- LIMKNRN2T1.f01 (steady flow) ---

Flow Title=Flow
Program Version=6.20
Number of Profiles= 1
Profile Names=P100yr
River Rch & RM=LIMKNRN2T1,Main            ,897
     343
Boundary for River Rch & Prof#=LIMKNRN2T1,Main            , 1
Up Type= 0
Dn Type= 1
Dn Known WS=2287.4
DSS Import GetInterval= 0
DSS Import GetPeak= 0
DSS Import FillOption= 0

--- LIMKNRN2T1.g01 (geometry) ---

Geom Title=Geometry
Program Version=6.20

River Reach=LIMKNRN2T1      ,Main
Reach XY= 30
2306739.65899999660510.7920000262306741.04799999660548.778000012
2306746.60400003660588.014000028      2306763.27660654.680999994
2306764.65899998660672.0419999962306761.55000003660712.598000035
2306745.56200001660752.2500000152306741.39500003660776.556000009
2306749.03400002660848.4309999942306764.31200001660885.931000024
     2306766.742660905.375000015      2306767.09660943.917000011
2306764.65899998660971.3470000182306751.11700003661032.806000009
     2306755.979661113.361000001     2306754.242661136.278000012
2306750.07600003661154.6809999942306737.86700003661184.841999993
2306729.41100001 661194.961000012306720.56200002661200.167000011
2306703.89500004661201.9030000122306664.65900002661196.695000008
2306648.68700002661199.1250000152306600.42300001661221.000000015
2306589.65899999661230.3750000152306584.79799999661243.570000008
2306585.14500003       661252.252306588.96500003661263.709000006
2306603.89500001661286.9720000032306601.83253688661303.675267469

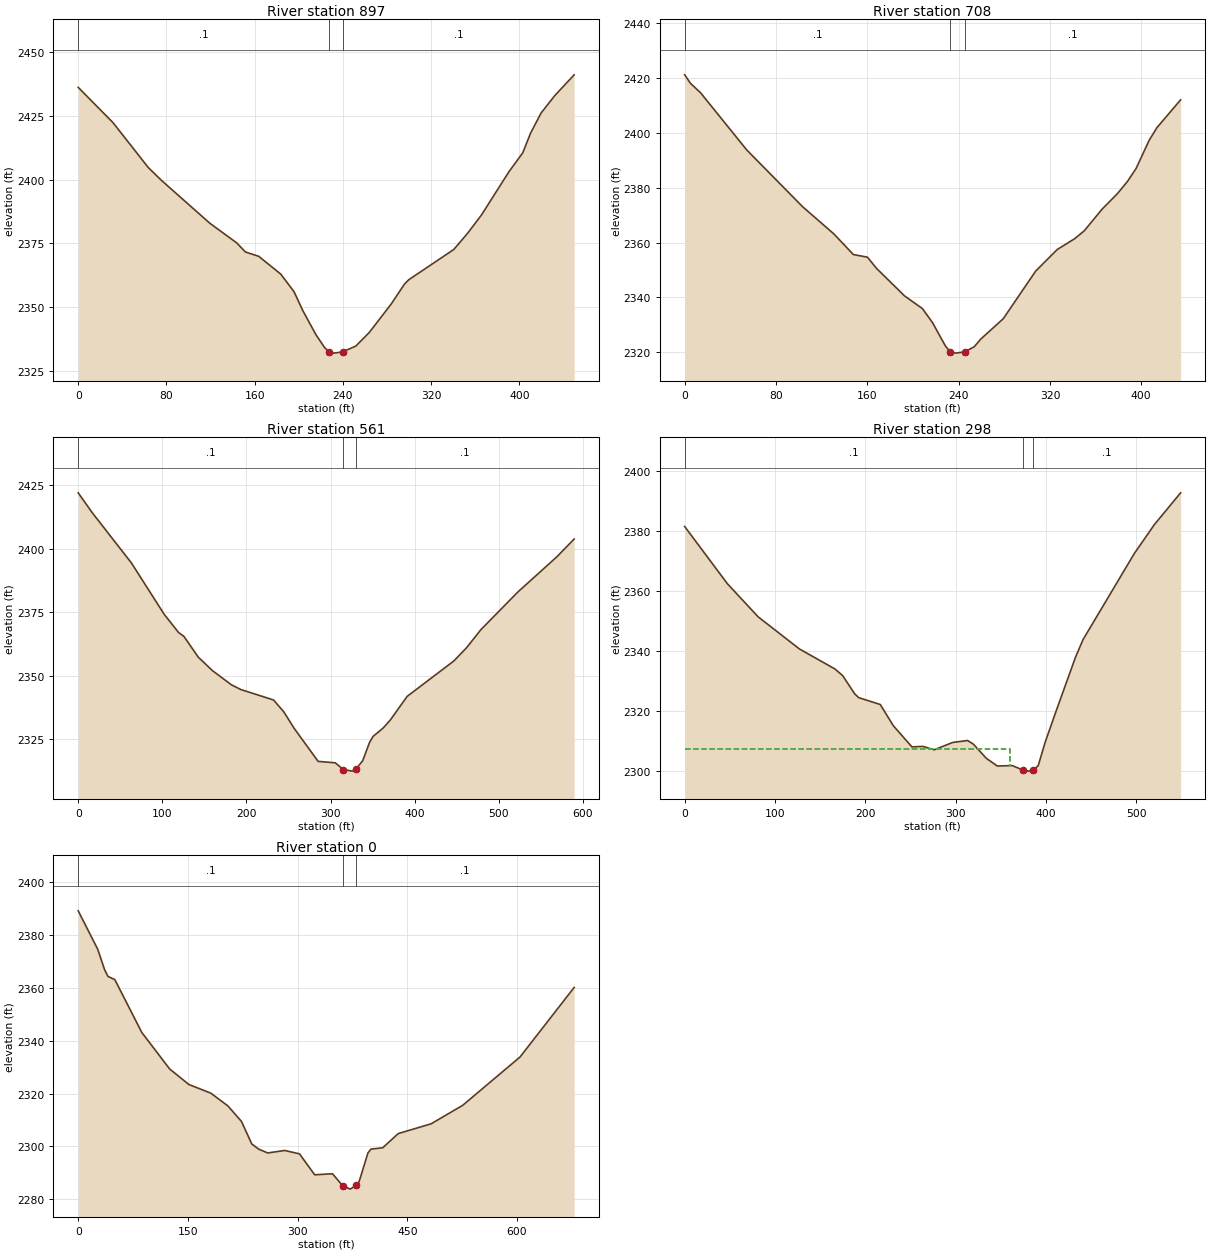
Type RM Length L Ch R = 1 ,897     ,189.1,189.1,189.1
XS GIS Cut Line= 3
2306508.61083627660536.6639011082306828.20177671660549.411118106
2306952.94240019660512.990498113
#Sta/Elev= 30
       0 2436.02    31.6 2422.21    63.6 2404.66    75.6 2399.62   119.4  2382.9
   143.7 2375.24   151.7 2371.66   163.7 2369.98   183.7 2363.02   195.7 2356.18
   203.7 2348.76   215.7 2339.27   223.7 2334.18   227.7 2332.62   231.7 2332.13
   239.8  2332.6   251.8  2334.9   263.8 2340.11   283.8 2351.28   295.8 2359.06
   299.8 2360.82   340.7 2372.67   353.2    2379   365.7 2386.11   390.7 2403.07
   403.2 2410.45   410.3 2418.15   419.8 2425.99   432.3 2432.84449.7938 2440.92
#Mann= 3 ,-1,0
       0      .1       0   227.7    .045       0   239.8      .1       0
Bank Sta=227.7,239.8
XS Rating Curve= 0 ,0
Exp/Cntr(USF)=0,0
Exp/Cntr=0.3,0.1

Type RM Length L Ch R = 1 ,708     ,147.3,147.3,147.3
XS GIS Cut Line= 4
2306531.37372377660658.6729780852306658.84589374660712.393392575
2306791.53869107660738.4778629492306927.44796619660652.299369586
#Sta/Elev= 30
       0  2421.1     5.2 2417.95    13.9 2414.58    54.4 2393.73   103.3 2373.07
   130.8 2363.12   147.8 2355.63   160.1 2354.69   168.2 2350.55   192.7 2340.55
   208.3 2335.95   217.1 2330.86   228.7 2322.15  232.77 2320.23   237.5 2319.73
   245.6 2320.21   253.8  2322.1   259.4 2324.84   279.1 2332.26   307.5  2349.6
   326.4 2357.48   341.6 2361.39   350.1 2364.29   365.6 2372.12   379.3  2377.9
     388 2382.31   395.5    2387   406.9 2397.22   413.8 2401.89   434.5    2412
#Mann= 3 ,0,0
       0      .1       0  232.77    .045       0   245.6      .1       0
Bank Sta=232.77,245.6
XS Rating Curve= 0 ,0
Exp/Cntr(USF)=0,0
Exp/Cntr=0.3,0.1

Type RM Length L Ch R = 1 ,561     ,262.9,262.9,262.9
XS GIS Cut Line= 4
2306502.23722777660741.5298885692306656.71274258660893.336676986
2306835.00201544660858.8404679222306997.55765968660960.053608527
#Sta/Elev= 30
       0 2422.08    16.6 2414.29    63.3 2394.46   102.2 2374.27   119.3 2367.09
   125.6 2365.59   142.9 2357.33   159.7 2352.05   182.1  2346.5   193.4 2344.63
   232.3 2340.51   244.6 2335.78   256.8 2329.34   285.3 2316.33   305.7 2315.77
   315.3 2313.12     326  2312.5330.24662313.248   338.3 2316.63   346.4 2323.77
   350.5 2326.13   362.7 2329.51   370.9 2332.54   391.2 2341.95   446.7 2355.89
   461.7 2361.07   479.1  2368.3   522.7 2383.01   569.2 2396.91   589.7  2403.9
#Mann= 3 ,0,0
       0      .1       0   315.3    .045       0330.2466      .1       0
Bank Sta=315.3,330.2466
XS Rating Curve= 0 ,0
Exp/Cntr(USF)=0,0
Exp/Cntr=0.3,0.1

Type RM Length L Ch R = 1 ,298     ,297.7,297.7,297.7
XS GIS Cut Line= 4
2306499.50568127660899.9595855392306594.19929325661094.809902502
2306806.34940471661145.7987704922306911.96920269  661102.0940265
#Sta/Elev= 30
       0 2381.62    47.3 2362.51    81.4 2351.43   127.1 2340.71   166.3 2334.05
     175  2331.8   188.1 2325.79   192.6 2324.47   216.6 2322.16     231 2315.09
   251.6 2308.01   263.9 2308.17   276.3 2307.03   296.8 2309.49   313.3 2310.14
   319.7 2308.91   333.9 2304.22   346.2 2301.61   362.7 2301.76     375 2300.23
   380.8 2299.91   386.1 2300.24   391.5 2301.77   399.3  2309.7     412 2320.57
   432.7 2337.92   441.1 2343.85   497.9 2372.61   520.1 2382.27549.1381 2392.87
#Mann= 3 ,-1,0
       0      .1       0     375    .045       0   386.1      .1       0
#XS Ineff= 2 , 0
          360.54 2307.29
Permanent Ineff=
       F       F
Bank Sta=375,386.1
XS Rating Curve= 0 ,0
Exp/Cntr(USF)=0,0
Exp/Cntr=0.3,0.1

Type RM Length L Ch R = 1 ,0       ,255.8,255.8,255.8
XS GIS Cut Line= 4
2306371.02177595661046.3347130122306520.01273238661291.448867144
2306659.39136905661312.2755599792306882.07677705661197.728749388
#Sta/Elev= 30
       0 2389.24    26.7 2374.68    36.1 2366.93    40.7 2364.39    50.1 2363.18
    86.9  2343.2     125 2329.36   151.4 2323.45   181.2 2320.21   204.6 2315.39
   223.3 2309.46   237.4 2300.93   246.7    2299   259.1 2297.54   282.4 2298.48
   302.6  2297.2   323.4 2289.26   347.7 2289.67  361.41 2285.21   371.9 2283.84
   380.1 2285.24   384.1 2286.64   396.2 2297.54   400.3 2298.98   416.4  2299.5
   437.6 2304.87   482.6 2308.58   525.7 2315.56   604.1 2333.86  678.19 2360.22
#Mann= 3 ,-1,0
       0      .1       0  361.41    .045       0   380.1      .1       0
Bank Sta=361.41,380.1
XS Rating Curve= 0 ,0
Exp/Cntr=0.3,0.1
LCMann Table=0

Chan Stop Cuts=-1
Use User Specified Reach Order=0
Composite Channel Slope=5